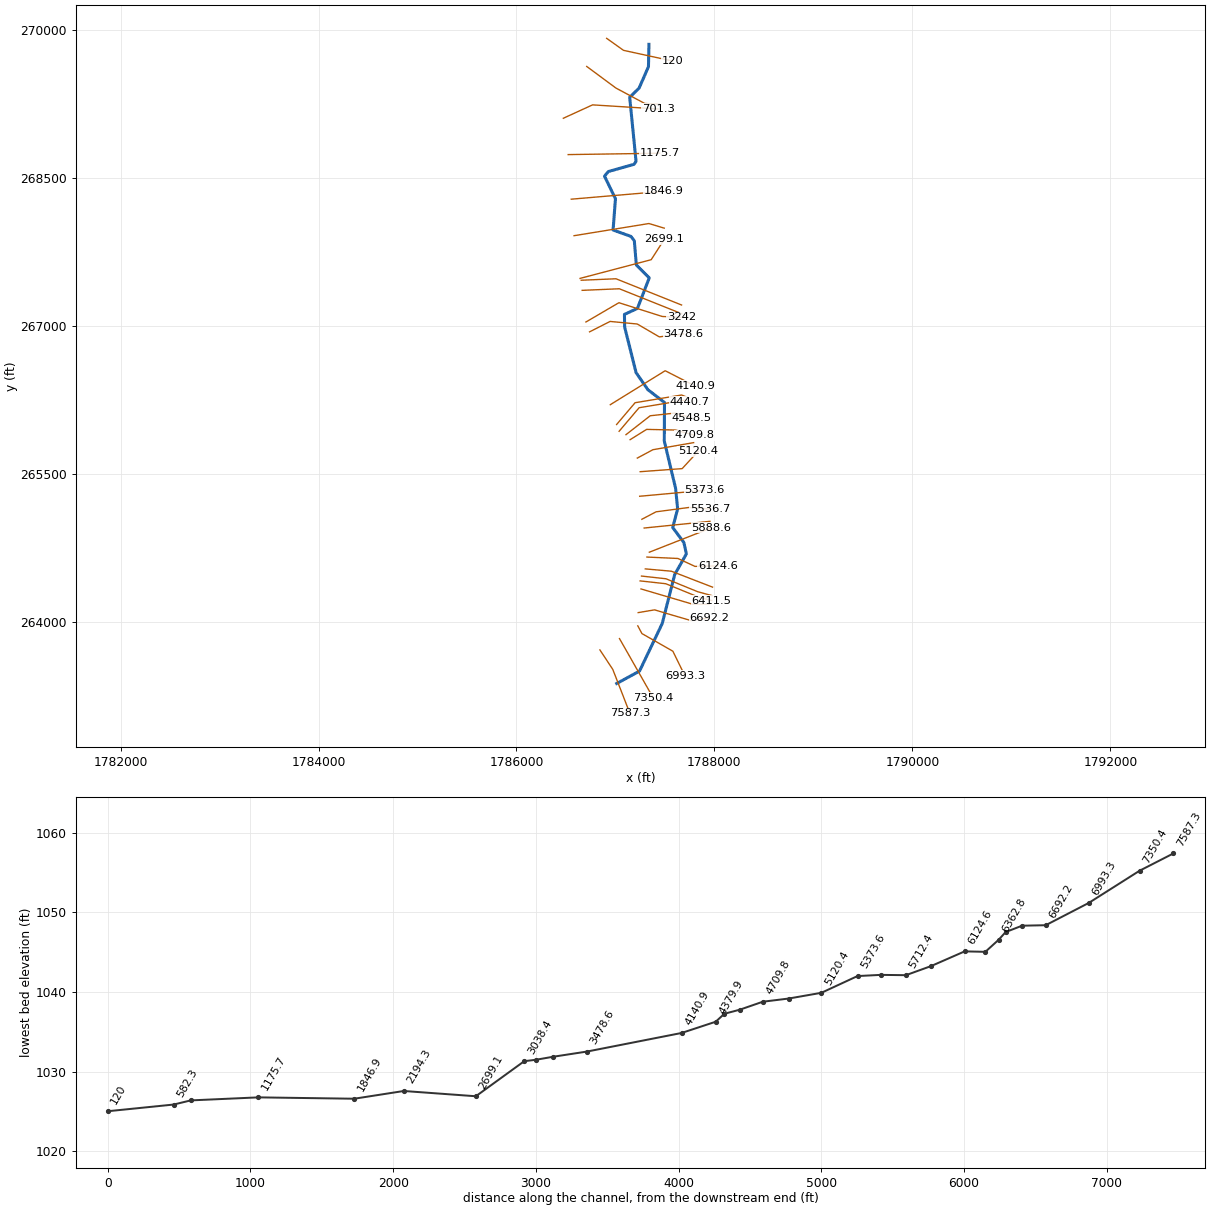
--- STILLHSRN.prj (project) ---

Proj Title=STILLHSRN
Current Plan=p01
Default Exp/Contr=0,0
English Units
Geom File=g01
Flow File=f01
Plan File=p01
BEGIN DESCRIPTION:
END DESCRIPTION:
DSS Export Rating Curves= 0
DSS Export Rating Curve Sorted= 0
DSS Export Volume Flow Curves= 0
DXF OffsetX= 0
DXF OffsetY= 0
DXF ScaleX= 0
DXF ScaleY= 0

--- STILLHSRN.p01 (plan) ---

Plan Title=Floodplain
Program Version=4.00
Geom File=g01
Flow File=f01
K Sum by GR=0
Std Step Tol=0.01
Critical Tol=0.01
Num of Std Step Trials=20
Max Error Tol=0.3
Flow Tol Ratio=0.001
Split Flow NTrial=30
Split Flow Tol=0.02
Split Flow Ratio=0.02
Log Output Level=0
Friction Slope Method=1
Unsteady Friction Slope Method=2
Unsteady Bridges Friction Slope Method=1
Global Log Level=0
CheckData=False
Run HTab=0
Run UNet=0
Run PostProcess=0
UNET Theta=0
UNET Theta Warmup=0
UNET ZTol=0
UNET ZSATol=0
UNET MxIter=0
UNET MaxInSteps=0
UNET DtIC=0
UNET DtMin=0
UNET MaxCRTS=0
UNET WFStab=0
UNET SFStab=0
UNET WFX=0
UNET SFX=0
UNET DSS MLevel=0
UNET DZMax Abort=0
UNET Convert EG Bridges=0
UNET Use Existing IB Tables=0
UNET Froude Limit=0
UNET Froude Power=0
Write IC File=0
Echo Input=False
Echo Output=False
Write Detailed=0

--- STILLHSRN.f01 (steady flow) ---

Flow Title=NFF Regression Equation
Program Version=4.00
Number of Profiles=1
Profile Names=P100yr
River Rch & RM=STILLHSRN,Main      ,7587.3
1380.793
River Rch & RM=STILLHSRN,Main      ,6526.7
1531.040
River Rch & RM=STILLHSRN,Main      ,3478.6
2919.336
River Rch & RM=STILLHSRN,Main      ,3478.6
1583.101
River Rch & RM=STILLHSRN,Main      ,582.3
3006.919
Boundary for River Rch & Prof#=STILLHSRN,Main      ,1
Up Type=0
Dn Type=3
Dn Slope=0.002314

--- STILLHSRN.g01 (geometry) ---

Geom Title=USGS 10m DEM
Program Version=4.10

River Reach=STILLHSRN       ,Main
Reach XY= 30
     1787013.016      263381.788     1787243.328      263507.348
     1787472.398      263988.109     1787598.541      264484.133
     1787716.769      264694.009     1787691.252      264809.546
     1787579.083      264960.625     1787628.504      265150.568
     1787607.664      265359.181     1787493.513      265837.537
     1787495.782      266226.737     1787327.947      266356.449
     1787209.039      266528.393     1787093.239      266990.017
     1787090.975      267118.788     1787222.724      267179.832
     1787341.461      267488.264     1787211.056      267620.063
      1787190.94      267863.067     1787157.445       267908.16
     1786976.124      267973.305     1787000.293      268289.513
     1786889.769      268518.192     1786928.543      268565.236
     1787187.669      268638.327     1787208.288      268668.004
     1787144.056      269317.033     1787238.694      269409.158
     1787333.681      269626.248     1787338.765      269853.309

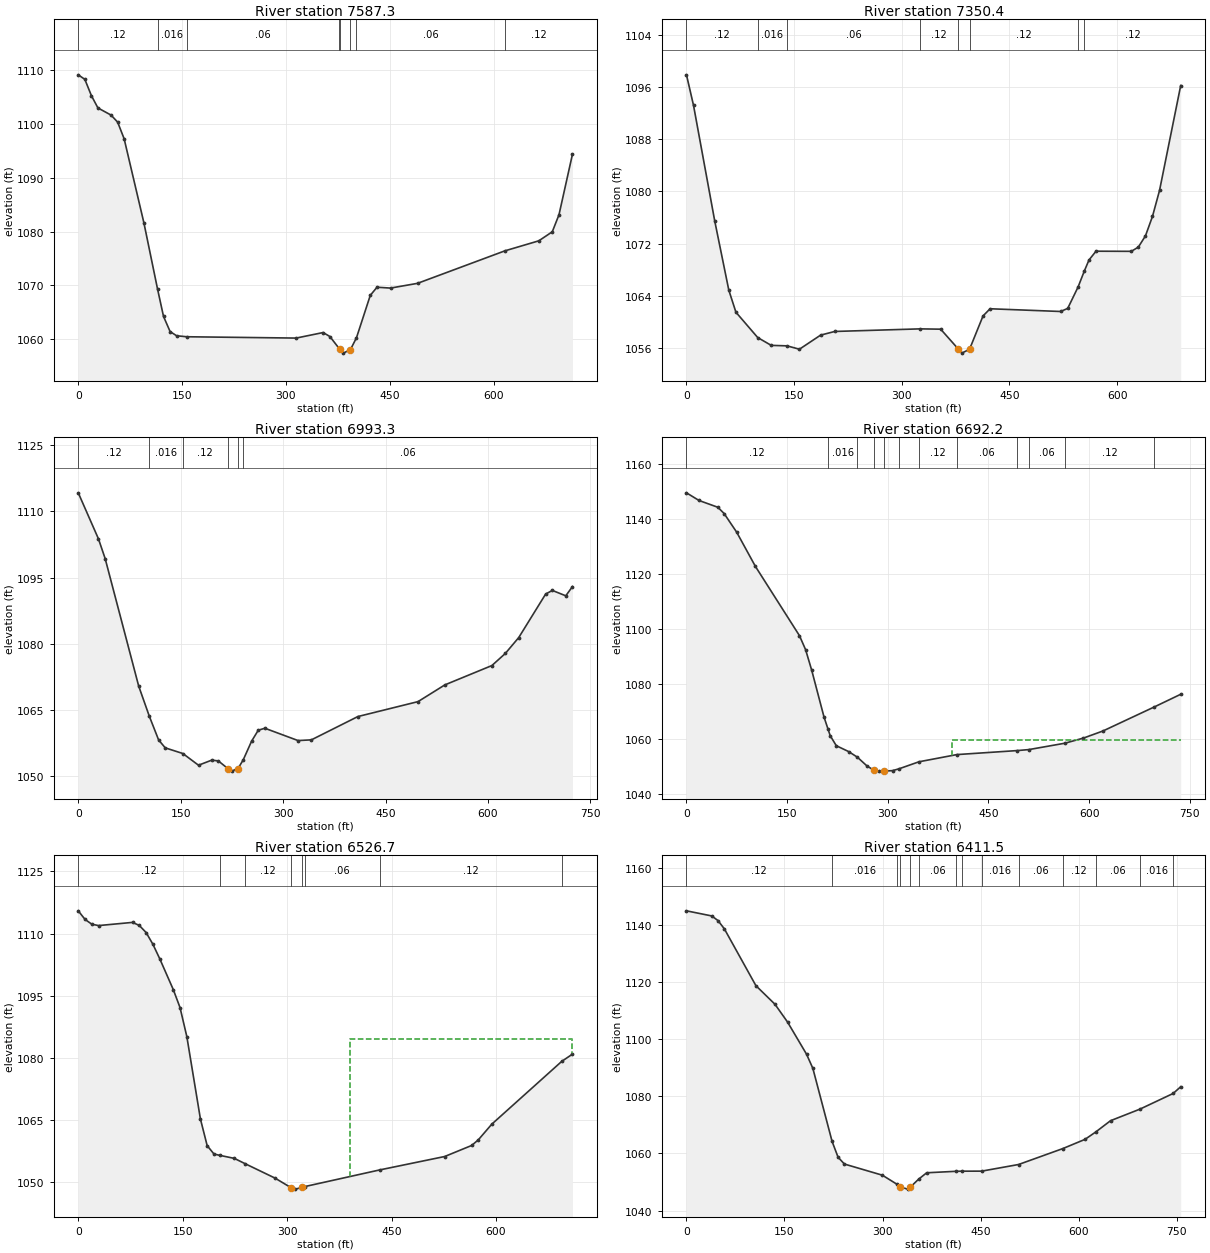
Type RM Length L Ch R = 1 ,7587.3  ,233.6,236.9,240.1
XS GIS Cut Line= 3
     1786843.246      263722.011     1786973.454      263524.094
     1787146.362      263079.426
#Sta/Elev= 30
       0 1109.16     9.5 1108.32      19 1105.29    28.4    1103    47.4 1101.67
    56.9 1100.36    66.3 1097.26    94.8 1081.65   114.6 1069.28   123.2 1064.21
   132.7  1061.4   142.1 1060.62   156.81060.435   314.8 1060.19   353.8 1061.22
   363.5 1060.48  376.251058.363   378.3 1058.07     383 1057.39   393.3 1058.06
  401.961060.258   421.9 1068.14   431.6 1069.65   451.1 1069.49   490.1 1070.37
  616.281076.414   665.3 1078.28   684.8 1079.96   694.5 1083.13     714 1094.41
#Mann= 8 ,-1 , 0
       0     .12       0   114.6    .016       0   156.8     .06       0
  376.25     .12       0   378.3    .045       0   393.3     .12       0
  401.96     .06       0  616.28     .12       0
Bank Sta=378.3,393.3
XS Rating Curve= 0 ,0
Exp/Cntr=0.3,0.1

Type RM Length L Ch R = 1 ,7350.4  ,344.8,357.1,369.3
XS GIS Cut Line= 2
     1787041.163      263836.594     1787381.006      263237.636
#Sta/Elev= 30
       0 1097.87     9.8  1093.2    39.4 1075.46      59 1064.87    68.9 1061.49
   99.281057.604   118.1 1056.41  140.051056.335   157.4 1055.82   186.9 1057.98
   206.6 1058.54   325.41058.938   354.2 1058.89  378.751055.846   383.7 1055.22
  394.461055.826   413.2 1060.92     423 1062.02   521.4  1061.6   531.2 1062.08
   545.71065.377  554.311067.799   560.8 1069.49   570.6 1070.84   619.8 1070.82
   629.6 1071.47   639.5 1073.19   649.3 1076.18   659.1 1080.15   688.6 1096.23
#Mann= 8 ,-1 , 0
       0     .12       0   99.28    .016       0  140.05     .06       0
   325.4     .12       0  378.75    .045       0  394.46     .12       0
   545.7     .06       0  554.31     .12       0
Bank Sta=378.75,394.46
XS Rating Curve= 0 ,0
Exp/Cntr=0.3,0.1

Type RM Length L Ch R = 1 ,6993.3  ,296,301.1,306.4
XS GIS Cut Line= 4
     1787226.058      263965.501     1787267.725      263887.376
     1787580.225       263708.99     1787701.319      263461.594
#Sta/Elev= 30
       0 1114.19    29.5  1103.8    39.4  1099.3    88.5 1070.43  104.181063.555
   117.7 1058.23   127.4 1056.44  153.151055.161   176.1 1052.51   195.5 1053.66
   205.2 1053.48     219 1051.76   224.7 1051.17     234 1051.76  241.641053.738
   253.9 1057.96   263.6 1060.43   273.3 1060.88   321.9 1058.09   341.4 1058.25
   409.5 1063.53   497.6 1066.91   536.9  1070.7   605.8 1075.08   625.4 1077.81
   645.1 1081.42   684.5 1091.27   694.3 1092.09     714 1090.87   723.8 1092.97
#Mann= 6 ,-1 , 0
       0     .12       0  104.18    .016       0  153.15     .12       0
     219    .045       0     234     .12       0  241.64     .06       0
Bank Sta=219,234
XS Rating Curve= 0 ,0
Exp/Cntr=0.3,0.1

Type RM Length L Ch R = 1 ,6692.2  ,165.3,165.5,165.3
XS GIS Cut Line= 5
     1787229.965      264099.615     1787395.913       264127.59
     1787510.089      264093.136     1787764.679      264018.676
     1787946.111      264047.532
#Sta/Elev= 30
       0 1149.49    18.7 1146.71    46.8 1144.24    56.1 1141.97    74.8  1135.2
   102.8 1122.73   168.3 1097.63   177.5 1092.52   186.6 1085.06     205 1068.01
  211.061063.557   214.2 1061.25   223.3 1057.61   241.7 1055.48  254.811053.421
   269.2 1050.21   280.1 1048.62   287.6 1048.38   295.1 1048.39   307.2 1048.57
  316.641049.215  346.351051.769  402.871054.387  492.771055.843  510.211056.206
  563.961058.523   591.5 1060.38   620.5 1062.95  697.151071.699   736.5  1076.3
#Mann= 12 ,-1 , 0
       0     .12       0  211.06    .016       0  254.81     .12       0
   280.1    .045       0   295.1     .12       0  316.64     .06       0
  346.35     .12       0  402.87     .06       0  492.77     .12       0
  510.21     .06       0  563.96     .12       0  697.15     .06       0
#XS Ineff= 2 , 0
                          395.46         1059.86
Permanent Ineff=
       F       F
Bank Sta=280.1,295.1
XS Rating Curve= 0 ,0
Exp/Cntr=0.3,0.1

Type RM Length L Ch R = 1 ,6526.7  ,117.7,115.2,112.9
XS GIS Cut Line= 3
     1787258.611      264339.198     1787782.048      264184.251
     1787946.111      264185.553
#Sta/Elev= 30
       0 1115.48     9.8  1113.4    19.5 1112.25    29.2 1111.92      78 1112.69
    87.7 1111.95    97.5 1110.24   107.2 1107.42     117 1103.94   136.5 1096.48
   146.2 1092.14     156 1085.11   175.5 1065.25   185.2 1058.81     195 1056.79
   203.61056.462   224.2 1055.74  239.841054.448   282.7 1050.98  305.721048.664
   311.9 1048.32   321.7 1048.73  325.761048.948  432.861052.948   526.4 1056.19
   565.2 1058.86   574.8 1060.23   594.1    1064  694.56 1079.15     710  1080.9
#Mann= 8 ,-1 , 0
       0     .12       0   203.6    .016       0  239.84     .12       0
  305.72    .045       0   321.7     .12       0  325.76     .06       0
  432.86     .12       0  694.56    .016       0
#XS Ineff= 2 , 0
                          390.51         1084.46
Permanent Ineff=
       F       F
Bank Sta=305.72,321.7
XS Rating Curve= 0 ,0
Exp/Cntr=0.3,0.1

Type RM Length L Ch R = 1 ,6411.5  ,48.6,48.7,48.8
XS GIS Cut Line= 4
     1787249.255       264420.71     1787508.692      264391.978
     1787831.609      264260.034     1787972.932      264221.609
#Sta/Elev= 30
       0 1144.86    38.7 1143.07    48.3 1141.44      58 1138.55   106.3 1118.67
   135.4 1112.19   154.7 1105.95   183.7 1094.73   193.4 1089.76  222.841064.205
     232 1058.68   241.7 1056.29   299.8 1052.39  322.281049.203   327.2 1048.28
   338.5 1047.52   342.2 1048.15  355.261051.001   367.6 1053.24  412.591053.755
  422.151053.799  451.731053.811  508.211056.133  576.041061.716   609.9 1064.93
  626.331067.515   648.9 1071.45  693.851075.493  744.751080.981   756.3 1083.33
#Mann= 14 ,-1 , 0
       0     .12       0  222.84    .016       0  322.28     .12       0
   327.2    .045       0   342.2     .12       0  355.26     .06       0
  412.59    .016       0  422.15     .12       0  451.73    .016       0
  508.21     .06       0  576.04     .12       0  626.33     .06       0
  693.85    .016       0  744.75     .12       0
Bank Sta=327.2,342.2
XS Rating Curve= 0 ,0
Exp/Cntr=0.3,0.1

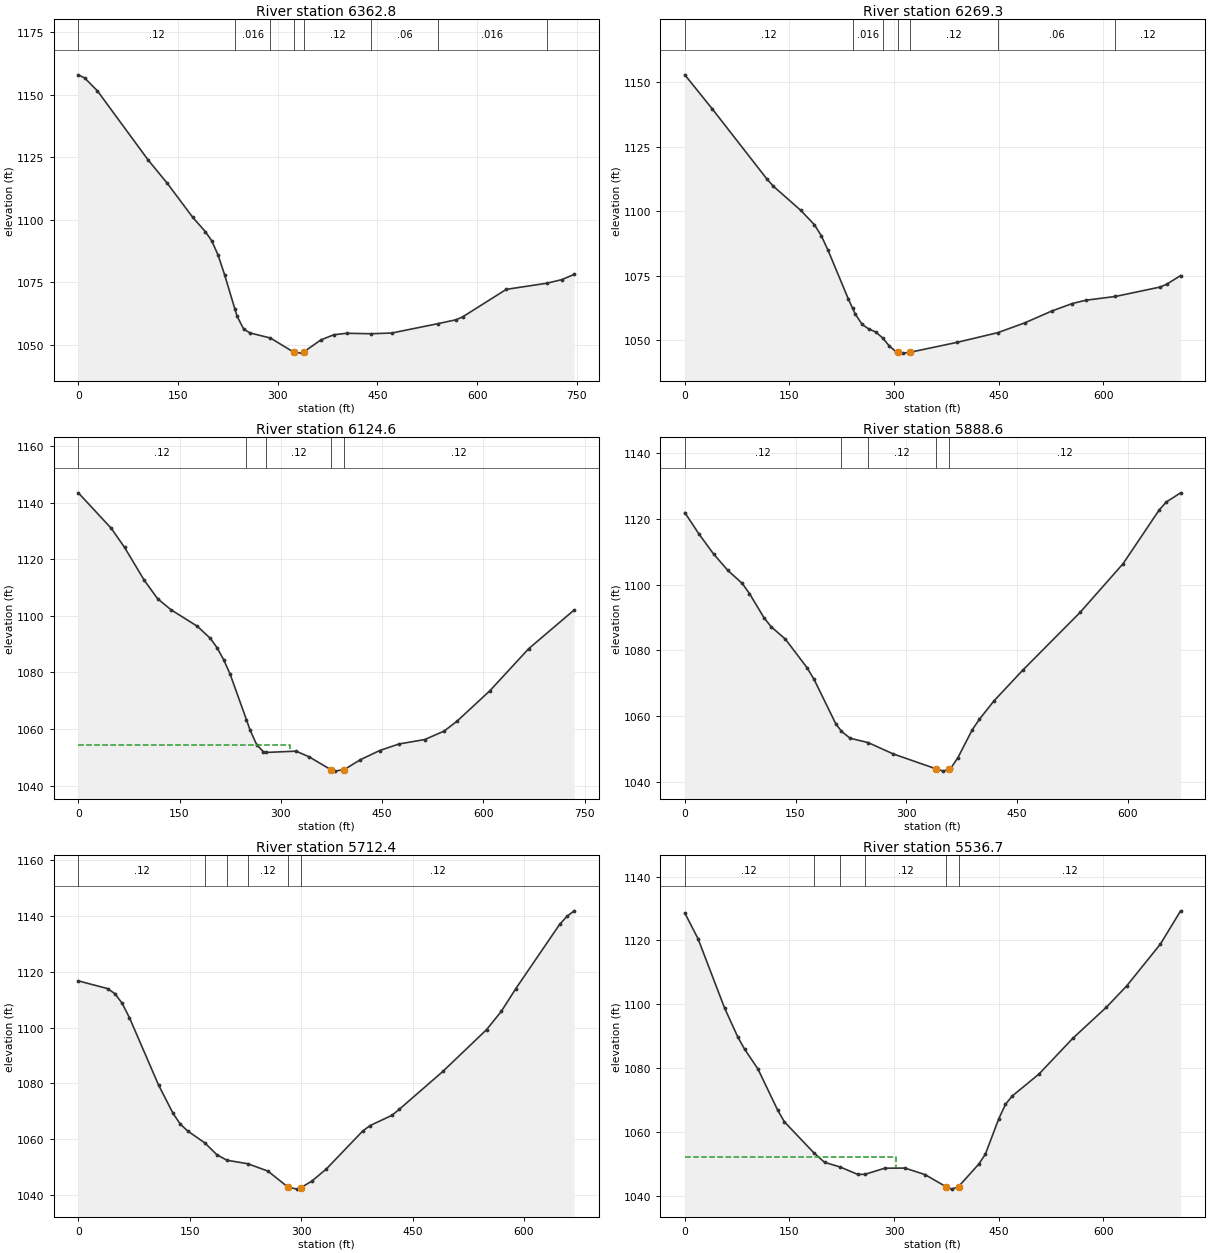
Type RM Length L Ch R = 1 ,6362.8  ,93,93.5,94
XS GIS Cut Line= 4
     1787263.252        264469.7     1787510.428      264442.325
     1787833.345      264310.381     1787976.714        264271.4
#Sta/Elev= 30
       0 1157.89     9.6 1156.62    28.7 1151.48   105.2 1123.77   133.9 1114.49
   172.2 1100.87   191.3 1095.11   200.9 1091.43   210.4 1085.72     220 1077.99
   235.81064.026   239.1 1061.23   248.7 1056.21   258.4 1054.63  289.081052.601
  323.881046.984   335.9 1046.56  339.641047.115     365 1051.85   384.4 1053.91
   403.7  1054.5  440.471054.318   471.6  1054.6  540.711058.328   568.4 1059.91
   578.1 1061.03     644 1072.07  705.221074.536   727.5 1075.96   746.1 1078.06
#Mann= 8 ,-1 , 0
       0     .12       0   235.8    .016       0  289.08     .12       0
  323.88    .045       0  339.64     .12       0  440.47     .06       0
  540.71    .016       0  705.22     .12       0
Bank Sta=323.88,339.64
XS Rating Curve= 0 ,0
Exp/Cntr=0.3,0.1

Type RM Length L Ch R = 1 ,6269.3  ,146.1,144.7,143.1
XS GIS Cut Line= 3
     1787301.579      264542.323       1787564.6      264518.886
     1787981.267      264357.428
#Sta/Elev= 30
       0 1152.75    39.1 1139.67   117.4 1112.54   127.1 1109.61   166.3 1100.29
   185.8 1094.76   195.6 1090.53   205.4 1084.84   234.7 1065.85  240.631062.383
   244.5 1060.12   254.3 1056.14   264.1 1054.33   273.8 1053.22  283.571050.937
   293.2 1047.82   302.9 1045.58   306.11045.402   312.6 1045.04   322.4 1045.34
   390.4 1049.21  448.691052.959   487.5 1056.76   526.4 1061.36   555.5 1064.23
   574.9 1065.51  617.261066.968   681.8 1070.63   691.5  1071.8   710.9 1075.07
#Mann= 7 ,-1 , 0
       0     .12       0  240.63    .016       0  283.57     .12       0
   306.1    .045       0   322.4     .12       0  448.69     .06       0
  617.26     .12       0
Bank Sta=306.1,322.4
XS Rating Curve= 0 ,0
Exp/Cntr=0.3,0.1

Type RM Length L Ch R = 1 ,6124.6  ,218.2,236,254.4
XS GIS Cut Line= 4
     1787318.221      264662.094     1787631.006      264647.792
     1787803.686       264567.49     1788034.652      264573.573
#Sta/Elev= 30
       0 1143.53    48.9 1130.95    68.5 1124.22    97.8 1112.56   117.4  1106.1
     137 1102.22   176.1 1096.37   195.7 1092.03   205.5 1088.74   215.3 1084.53
     225 1079.32  248.991063.344   254.4 1059.64   264.2 1054.48     274 1051.97
  278.621051.715   322.6 1052.16   341.7 1050.19  374.711045.535   379.8  1045.1
  393.851045.631   417.8 1049.13   446.4 1052.38     475  1054.7   513.2 1056.27
   542.1 1059.28   561.3 1062.82   609.4 1073.45   667.2  1088.4   734.6 1102.09
#Mann= 5 ,-1 , 0
       0     .12       0  248.99    .016       0  278.62     .12       0
  374.71    .045       0  393.85     .12       0
#XS Ineff= 2 , 0
          313.73 1054.39
Permanent Ineff=
       F       F
Bank Sta=374.71,393.85
XS Rating Curve= 0 ,0
Exp/Cntr=0.3,0.1

Type RM Length L Ch R = 1 ,5888.6  ,181.7,176.2,169.9
XS GIS Cut Line= 2
     1787342.465       264711.16     1787967.465      264957.254
#Sta/Elev= 30
       0 1121.94    19.5 1115.32    38.9 1109.37    58.4 1104.32    77.9 1100.36
    87.6  1097.3   107.1    1090   116.8 1087.24   136.3 1083.41   165.5 1074.76
   175.2 1071.14   204.4 1057.72  212.231055.363   223.9 1053.27  248.491051.922
   282.3 1048.49   340.7 1043.92   350.4 1043.25   358.3 1043.94   360.2  1044.1
   369.9 1047.32   389.4 1055.83   399.1 1059.03   418.6 1064.57   457.5  1073.9
   535.4 1091.53   593.8  1106.4   642.5 1122.68   652.2 1125.15   671.7 1127.95
#Mann= 5 ,-1 , 0
       0     .12       0  212.23    .016       0  248.49     .12       0
   340.7    .045       0   358.3     .12       0
Bank Sta=340.7,358.3
XS Rating Curve= 0 ,0
Exp/Cntr=0.3,0.1

Type RM Length L Ch R = 1 ,5712.4  ,174.9,175.7,176.2
XS GIS Cut Line= 2
     1787290.381      264955.952     1787954.444       265023.66
#Sta/Elev= 30
       0 1116.77    39.3    1114    49.1 1112.22    58.9 1108.77    68.7 1103.63
     108 1079.44   127.6 1069.23   137.4 1065.39   147.2 1062.96  170.271058.681
   186.5 1054.46  200.011052.467  228.141051.215   255.2 1048.58   282.2 1042.84
   294.5 1042.11  299.791042.685   314.1 1044.92   333.8 1049.32   382.8 1062.92
   392.6 1064.88   422.1 1068.56   431.9 1070.68   490.8 1084.32   549.7 1099.32
   569.3  1105.8     589 1114.01   647.9    1137   657.7 1139.86   667.5 1141.88
#Mann= 6 ,-1 , 0
       0     .12       0  170.27     .08       0  200.01    .016       0
  228.14     .12       0   282.2    .045       0  299.79     .12       0
Bank Sta=282.2,299.79
XS Rating Curve= 0 ,0
Exp/Cntr=0.3,0.1

Type RM Length L Ch R = 1 ,5536.7  ,164,163.1,162.2
XS GIS Cut Line= 4
     1787266.944      265044.494     1787410.173      265120.014
     1787743.506      265164.285     1787955.746       265148.66
#Sta/Elev= 30
       0  1128.6      19 1120.52    57.2 1098.77    76.2 1089.69    85.7 1085.98
   104.8  1079.8   133.4 1066.78   142.9  1063.2  184.661053.601   200.4 1050.54
  222.541049.091   248.4 1046.73  258.541046.803   286.8  1048.7   315.6 1048.74
   344.5  1046.7   374.8 1042.88   382.9 1042.15   392.5 1042.94   421.3 1049.92
   430.9 1053.04   450.1 1064.11   459.8 1068.67   469.4 1071.28   507.8 1078.16
   556.2 1089.33   604.6  1099.1   633.6 1105.75     682 1118.86     711 1129.27
#Mann= 6 ,-1 , 0
       0     .12       0  184.66    .016       0  222.54     .06       0
  258.54     .12       0   374.8    .045       0   392.5     .12       0
#XS Ineff= 2 , 0
          302.17 1052.16
Permanent Ineff=
       F       F
Bank Sta=374.8,392.5
XS Rating Curve= 0 ,0
Exp/Cntr=0.3,0.1

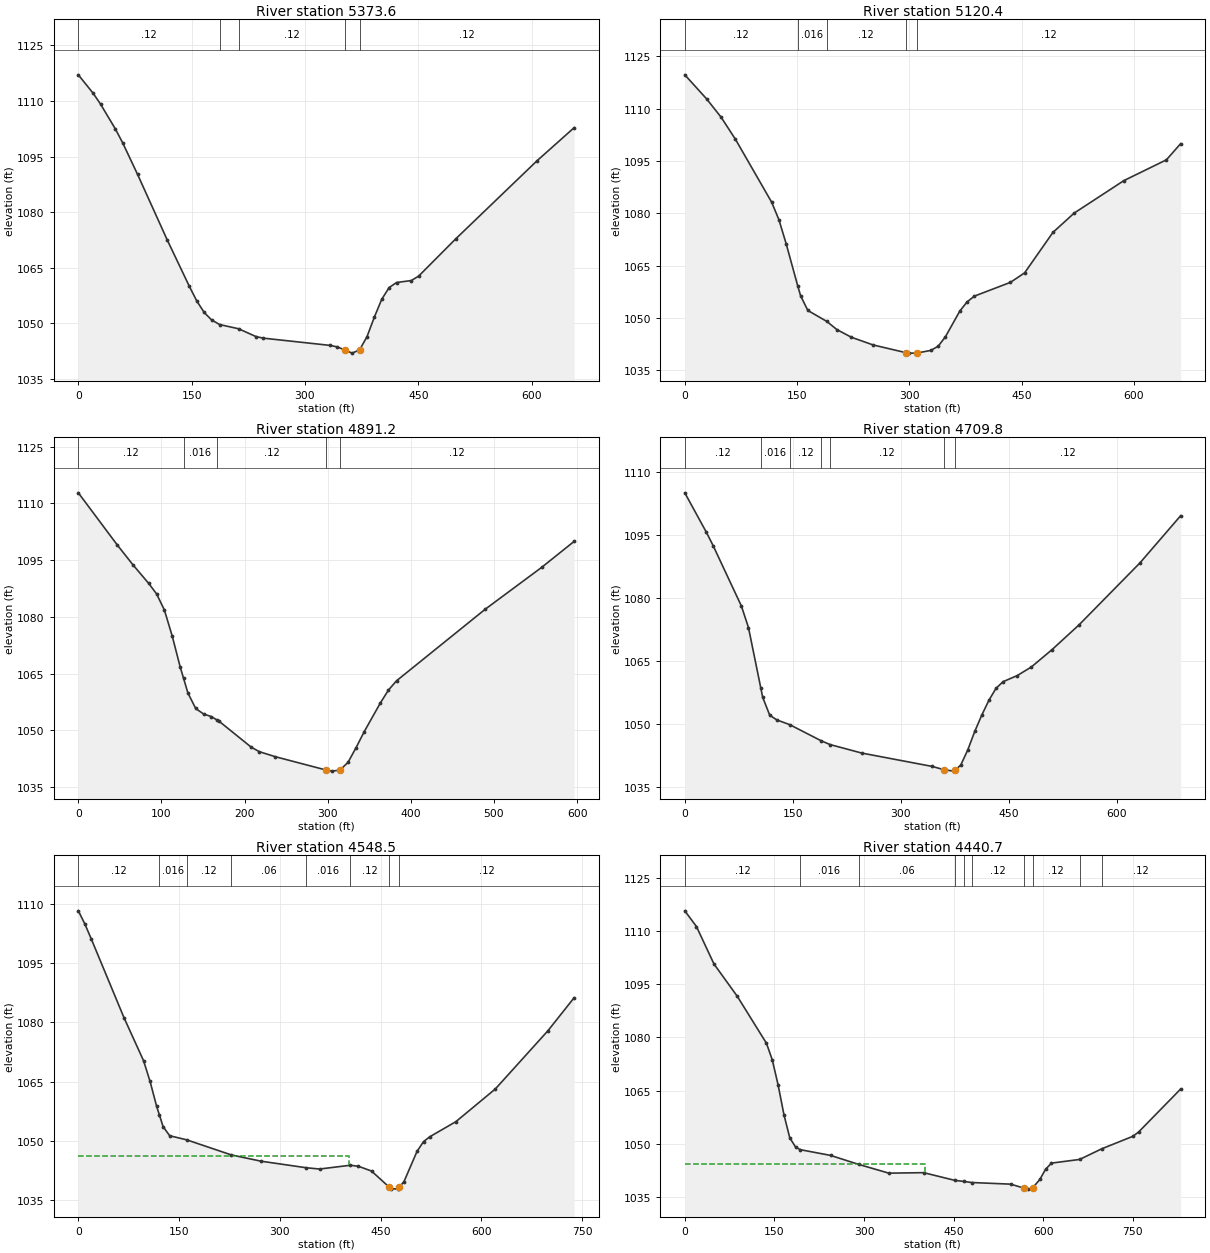
Type RM Length L Ch R = 1 ,5373.6  ,253.4,253.2,252.7
XS GIS Cut Line= 2
     1787244.808      265277.566     1787898.454      265337.462
#Sta/Elev= 30
       0 1117.07    19.6  1112.1    29.4 1109.17      49 1102.48    58.8 1098.69
    78.4 1090.22   117.6 1072.57     147    1060   156.8 1056.07   166.6 1052.97
   176.3 1050.98  187.051049.708  212.191048.573   235.1 1046.47   244.9 1046.04
   333.1 1044.09   342.9 1043.68   352.7 1042.86   362.5    1042   372.3 1042.88
   382.1  1046.4   391.9 1051.72   401.7 1056.54   411.5 1059.69   421.3 1061.05
   440.9 1061.58   450.6 1062.79   499.6 1072.82   607.4 1093.92   656.4 1102.82
#Mann= 5 ,-1 , 0
       0     .12       0  187.05    .016       0  212.19     .12       0
   352.7    .045       0   372.3     .12       0
Bank Sta=352.7,372.3
XS Rating Curve= 0 ,0
Exp/Cntr=0.3,0.1

Type RM Length L Ch R = 1 ,5120.4  ,227,229.2,231.3
XS GIS Cut Line= 3
     1787250.017      265526.264     1787674.496      265557.514
     1787834.652      265731.994
#Sta/Elev= 30
       0 1119.65      29 1112.79    48.4 1107.54    67.7 1101.17   116.1 1083.13
   125.8  1078.1   135.4 1071.27  151.061059.034   154.8  1056.3   164.4 1052.13
  189.911048.965   203.1 1046.66   222.5 1044.46   251.5 1042.25  295.011040.055
   299.9  1039.9   309.6  1039.9   328.9 1040.69   338.6 1041.89   348.2 1044.58
   367.6    1052   377.3  1054.6   386.9 1056.23   435.1 1060.18     454 1062.89
   491.9  1074.5   520.4 1080.05   586.7 1089.34   643.5 1095.29   662.5 1099.92
#Mann= 5 ,-1 , 0
       0     .12       0  151.06    .016       0  189.91     .12       0
  295.01    .045       0   309.6     .12       0
Bank Sta=295.01,309.6
XS Rating Curve= 0 ,0
Exp/Cntr=0.3,0.1

Type RM Length L Ch R = 1 ,4891.2  ,185.8,181.4,177.1
XS GIS Cut Line= 3
     1787221.371      265664.285     1787378.923      265748.921
     1787790.381      265820.535
#Sta/Elev= 30
       0 1112.81    47.1 1098.94    65.9 1093.71    84.7 1088.84    94.1 1086.08
   103.5 1081.83     113 1074.88   122.4 1066.85  126.621063.716   131.8 1059.87
   141.2 1055.75   150.6 1054.31     160 1053.61  166.67 1052.73   169.4 1052.37
     208 1045.52   217.7 1044.33   237.1 1042.99  298.311039.458   305.1 1039.18
   314.8 1039.46   324.5 1041.52   334.2 1045.42     344 1049.65   363.4 1057.23
   373.1 1060.63   382.8 1063.08   489.6 1082.03   557.6 1093.12   596.5 1099.97
#Mann= 5 ,-1 , 0
       0     .12       0  126.62    .016       0  166.67     .12       0
  298.31    .045       0   314.8     .12       0
Bank Sta=298.31,314.8
XS Rating Curve= 0 ,0
Exp/Cntr=0.3,0.1

Type RM Length L Ch R = 1 ,4709.8  ,158.3,161.3,164.3
XS GIS Cut Line= 4
     1787148.454      265850.483     1787315.121       265954.65
     1787609.392      265948.139     1787799.496      265894.754
#Sta/Elev= 30
       0 1104.99    29.5 1095.75    39.3 1092.44    78.6 1078.04    88.4 1072.93
  105.391058.651   108.1 1056.37   117.9 1052.08   127.8 1050.96  145.561049.846
  189.431045.991  201.721045.097   245.6 1043.08   343.7 1039.89  359.231039.138
   373.2 1038.78  375.491039.109     383 1040.19   392.8 1043.82   402.6 1048.26
   412.4 1052.16   422.2 1055.65     432 1058.47   441.8 1060.06   461.4  1061.5
   481.1 1063.56   509.7 1067.67   547.3 1073.58   631.9 1088.33   688.3 1099.54
#Mann= 7 ,-1 , 0
       0     .12       0  105.39    .016       0  145.56     .12       0
  189.43     .06       0  201.72     .12       0  359.23    .045       0
  375.49     .12       0
Bank Sta=359.23,375.49
XS Rating Curve= 0 ,0
Exp/Cntr=0.3,0.1

Type RM Length L Ch R = 1 ,4548.5  ,106.5,107.8,109
XS GIS Cut Line= 4
     1787106.788      265901.264     1787351.579      266092.671
     1787601.579      266120.014      1787770.85      266071.837
#Sta/Elev= 30
       0 1108.27     9.7 1104.95    19.4 1101.09      68  1081.2    97.1 1070.31
   106.8 1065.06   116.5  1058.8  120.511056.659   126.2 1053.62     136  1051.3
  161.241050.273  227.741046.447   271.9 1044.86   339.31043.196   359.1 1042.87
  405.11 1043.83   417.1 1043.56   436.5 1042.36  462.231038.381   465.5 1037.92
   475.2 1037.78  478.031038.339   484.8 1039.67   504.2 1047.32   513.9 1049.81
   523.5 1051.07   562.2 1054.88   620.9 1063.16   699.1 1077.89   738.2 1086.27
#Mann= 8 ,-1 , 0
       0     .12       0  120.51    .016       0  161.24     .12       0
  227.74     .06       0   339.3    .016       0  405.11     .12       0
  462.23    .045       0  478.03     .12       0
#XS Ineff= 2 , 0
          402.89 1046.22
Permanent Ineff=
       F       F
Bank Sta=462.23,478.03
XS Rating Curve= 0 ,0
Exp/Cntr=0.3,0.1

Type RM Length L Ch R = 1 ,4440.7  ,64.6,60.8,59.4
XS GIS Cut Line= 4
     1787037.233      265935.329     1787238.944      266173.879
     1787708.996      266252.004     1787747.325      266236.782
#Sta/Elev= 30
       0 1115.68    19.5 1111.26    48.8 1100.72    87.9 1091.59   136.7 1078.37
   146.4 1073.72   156.2 1066.64     166 1058.23   175.7 1051.74   185.5 1049.11
  193.421048.383   244.1 1046.77     2911044.242   341.6 1041.77   399.9 1041.91
  451.881039.748  467.071039.438  480.521039.131   545.8 1038.67   567.6 1037.55
     575 1037.27   582.6 1037.67   594.4 1039.99   604.1 1042.89   613.9  1044.6
  660.981045.633  698.231048.646     750 1052.14   759.7 1053.35   830.1 1065.47
#Mann= 10 ,-1 , 0
       0     .12       0  193.42    .016       0     291     .06       0
  451.88     .12       0  467.07     .06       0  480.52     .12       0
   567.6    .045       0   582.6     .12       0  660.98     .06       0
  698.23     .12       0
#XS Ineff= 2 , 0
          401.44 1044.49
Permanent Ineff=
       F       F
Bank Sta=567.6,582.6
XS Rating Curve= 0 ,0
Exp/Cntr=0.3,0.1

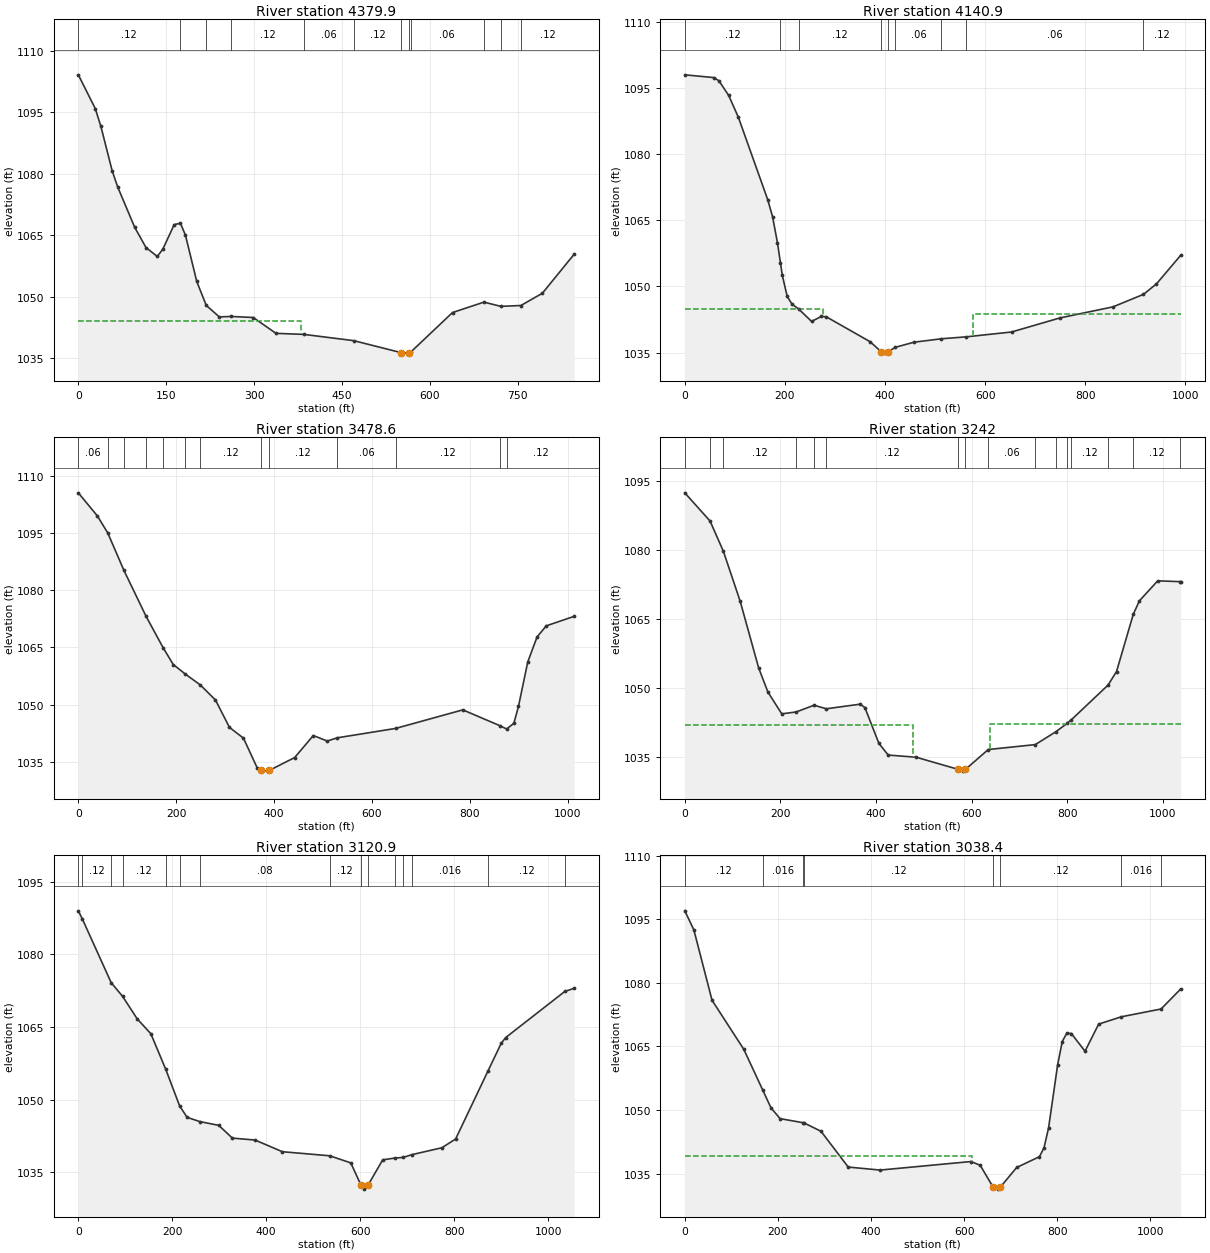
Type RM Length L Ch R = 1 ,4379.9  ,226.3,239,249.1
XS GIS Cut Line= 4
     1787012.084      266004.104     1787198.579       266224.66
     1787668.631      266302.785     1787744.202      266272.773
#Sta/Elev= 30
       0 1104.08    28.9 1095.86    38.5 1091.52    57.8 1080.67    67.4 1076.68
    96.3 1066.91   115.5    1062   134.8 1059.82   144.4 1061.63   163.7 1067.59
   174.31067.912   182.9 1065.01   202.2 1053.73  218.461047.893   240.7  1045.1
  261.261045.203   298.6 1044.95   337.5 1041.09  385.251040.834  470.321039.307
   551.4 1036.38   561.1 1036.27  564.271036.384  567.361036.496   638.9 1046.16
  692.531048.695  721.521047.666  755.651047.872   792.4 1050.87   846.6 1060.37
#Mann= 12 ,-1 , 0
       0     .12       0   174.3     .08       0  218.46    .016       0
  261.26     .12       0  385.25     .06       0  470.32     .12       0
   551.4    .045       0  564.27     .12       0  567.36     .06       0
  692.53     .12       0  721.52     .06       0  755.65     .12       0
#XS Ineff= 2 , 0
          379.77 1044.05
Permanent Ineff=
       F       F
Bank Sta=551.4,564.27
XS Rating Curve= 0 ,0
Exp/Cntr=0.3,0.1

Type RM Length L Ch R = 1 ,4140.9  ,676.9,662.2,647.5
XS GIS Cut Line= 3
     1786947.933       266204.65     1787502.621        266548.4
     1787803.402      266394.754
#Sta/Elev= 30
       0 1097.96    58.4 1097.33    68.2  1096.6    87.7 1093.28   107.1  1088.3
   165.6 1069.66   175.3 1065.79   185.1 1059.85  191.041055.331   194.8 1052.47
   204.5 1047.72   214.3 1045.95  227.131044.895   253.2 1042.05   272.7 1043.18
   282.4 1043.11   370.1 1037.45  392.141035.203   399.3 1034.86  406.331035.212
  420.511036.179   457.8 1037.34  512.561038.114  561.961038.551   652.6 1039.65
   749.1 1042.84   855.2 1045.35   916.11048.184   942.1 1050.57   990.3 1057.02
#Mann= 9 ,-1 , 0
       0     .12       0  191.04    .016       0  227.13     .12       0
  392.14    .045       0  406.33     .12       0  420.51     .06       0
  512.56     .12       0  561.96     .06       0   916.1     .12       0
#XS Ineff= 2 , 0
          275.54 1044.78  574.82         1043.83
Permanent Ineff=
       F       F
Bank Sta=392.14,406.33
XS Rating Curve= 0 ,0
Exp/Cntr=0.3,0.1

Type RM Length L Ch R = 1 ,3478.6  ,238.4,236.6,231.6
XS GIS Cut Line= 5
     1786738.629      266942.019     1786945.975      267047.577
     1787220.714      267021.535     1787443.371      266891.327
     1787687.912      266921.588
#Sta/Elev= 30
       0 1105.62    38.8 1099.57   60.02 1095.11   93.211085.234  138.421073.186
  173.041064.985   193.9 1060.53  217.961058.084  249.261055.157   280.2  1051.2
   308.8 1044.02   337.4 1041.18   365.9 1033.26  373.071032.707   375.4 1032.53
  390.041032.713     442  1036.1   480.1 1041.88   508.6 1040.43  528.741041.272
  648.391043.748   785.5 1048.62  861.89 1044.43  874.971043.595   889.8 1045.08
   899.2 1049.52   918.2 1061.19   937.2 1067.77   956.1 1070.69    1013 1073.18
#Mann= 13 ,-1 , 0
       0     .06       0   60.02     .12       0   93.21    .016       0
  138.42     .12       0  173.04    .016       0  217.96     .08       0
  249.26     .12       0  373.07    .045       0  390.04     .12       0
  528.74     .06       0  648.39     .12       0  861.89     .06       0
  874.97     .12       0
Bank Sta=373.07,390.04
XS Rating Curve= 0 ,0
Exp/Cntr=0.3,0.1

Type RM Length L Ch R = 1 ,3242    ,125.3,121.1,119.3
XS GIS Cut Line= 4
      1786701.84      267041.889     1787035.173      267237.202
     1787472.673      267097.879     1787664.079      267088.764
#Sta/Elev= 30
       0 1092.35   52.891086.211   80.861079.606   115.9 1068.77   154.5  1054.3
   173.8 1049.07   202.8 1044.33  232.721044.729  270.41  1046.2     2961045.427
     367 1046.43   376.7 1045.69   405.9 1037.93   425.4 1035.37     484  1034.9
     572 1032.26   581.7 1031.88  586.96 1032.25  634.731036.575  733.121037.643
  776.361040.453  800.211042.303  808.431043.028   885.21050.565     903 1053.51
     9381065.935   950.9 1068.89   989.2 1073.23 1034.811073.057  1037.1 1073.05
#Mann= 16 ,-1 , 0
       0     .12       0   52.89    .016       0   80.86     .12       0
  232.72    .016       0  270.41     .06       0     296     .12       0
     572    .045       0  586.96     .12       0  634.73     .06       0
  733.12    .016       0  776.36     .08       0  800.21    .016       0
  808.43     .12       0   885.2    .016       0     938     .12       0
 1034.81     .06       0
#XS Ineff= 2 , 0
          478.02 1041.82  637.77         1042.18
Permanent Ineff=
       F       F
Bank Sta=572,586.96
XS Rating Curve= 0 ,0
Exp/Cntr=0.3,0.1

Type RM Length L Ch R = 1 ,3120.9  ,82.2,82.5,82.3
XS GIS Cut Line= 3
     1786663.899      267362.373     1787039.725      267378.306
     1787670.222      267125.493
#Sta/Elev= 30
       0 1088.99    8.461087.324   69.911074.154   94.381071.301   125.4 1066.66
   154.3 1063.61  185.981056.273  215.571048.708   231.5 1046.33  258.431045.458
     299 1044.67   327.9 1042.04   376.2 1041.64   434.4 1039.23  535.061038.388
     580 1036.92   601.5 1032.36   609.1  1031.5   616.5 1032.28   647.9 1037.55
  674.24 1037.92  691.541038.055  710.421038.631     774 1040.05   803.2 1041.86
   872.41055.979   900.2 1061.62   909.9 1062.82 1035.541072.334  1055.5 1072.98
#Mann= 15 ,-1 , 0
       0    .016       0    8.46     .12       0   69.91     .06       0
   94.38     .12       0  185.98     .06       0  215.57    .016       0
  258.43     .08       0  535.06     .12       0   601.5    .045       0
   616.5     .12       0  674.24    .016       0  691.54     .08       0
  710.42    .016       0   872.4     .12       0 1035.54     .06       0
Bank Sta=601.5,616.5
XS Rating Curve= 0 ,0
Exp/Cntr=0.3,0.1

Type RM Length L Ch R = 1 ,3038.4  ,324.2,339.3,354.3
XS GIS Cut Line= 3
     1786654.567      267464.737      1787005.35      267479.608
     1787668.151      267213.842
#Sta/Elev= 30
       0 1097.03    19.5 1092.52    58.5 1075.92   126.8 1064.32  167.451054.709
   185.3 1050.48   204.8 1047.96   252.91047.029  255.791046.975   292.6 1044.98
   351.1 1036.53   419.6 1035.82   615.2 1037.84   634.8 1036.92  662.29  1031.8
   673.9 1031.32  678.08 1031.81     713 1036.43     762 1038.99   771.7 1041.08
   781.5 1045.77   801.1 1060.74   810.9 1066.17   820.6 1068.14   830.4 1068.06
   859.8 1063.88   889.1 1070.28  937.731072.009 1023.191073.854  1065.2 1078.56
#Mann= 8 ,-1 , 0
       0     .12       0  167.45    .016       0   252.9     .08       0
  255.79     .12       0  662.29    .045       0  678.08     .12       0
  937.73    .016       0 1023.19     .06       0
#XS Ineff= 2 , 0
          617.96  1039.1
Permanent Ineff=
       F       F
Bank Sta=662.29,678.08
XS Rating Curve= 0 ,0
Exp/Cntr=0.3,0.1

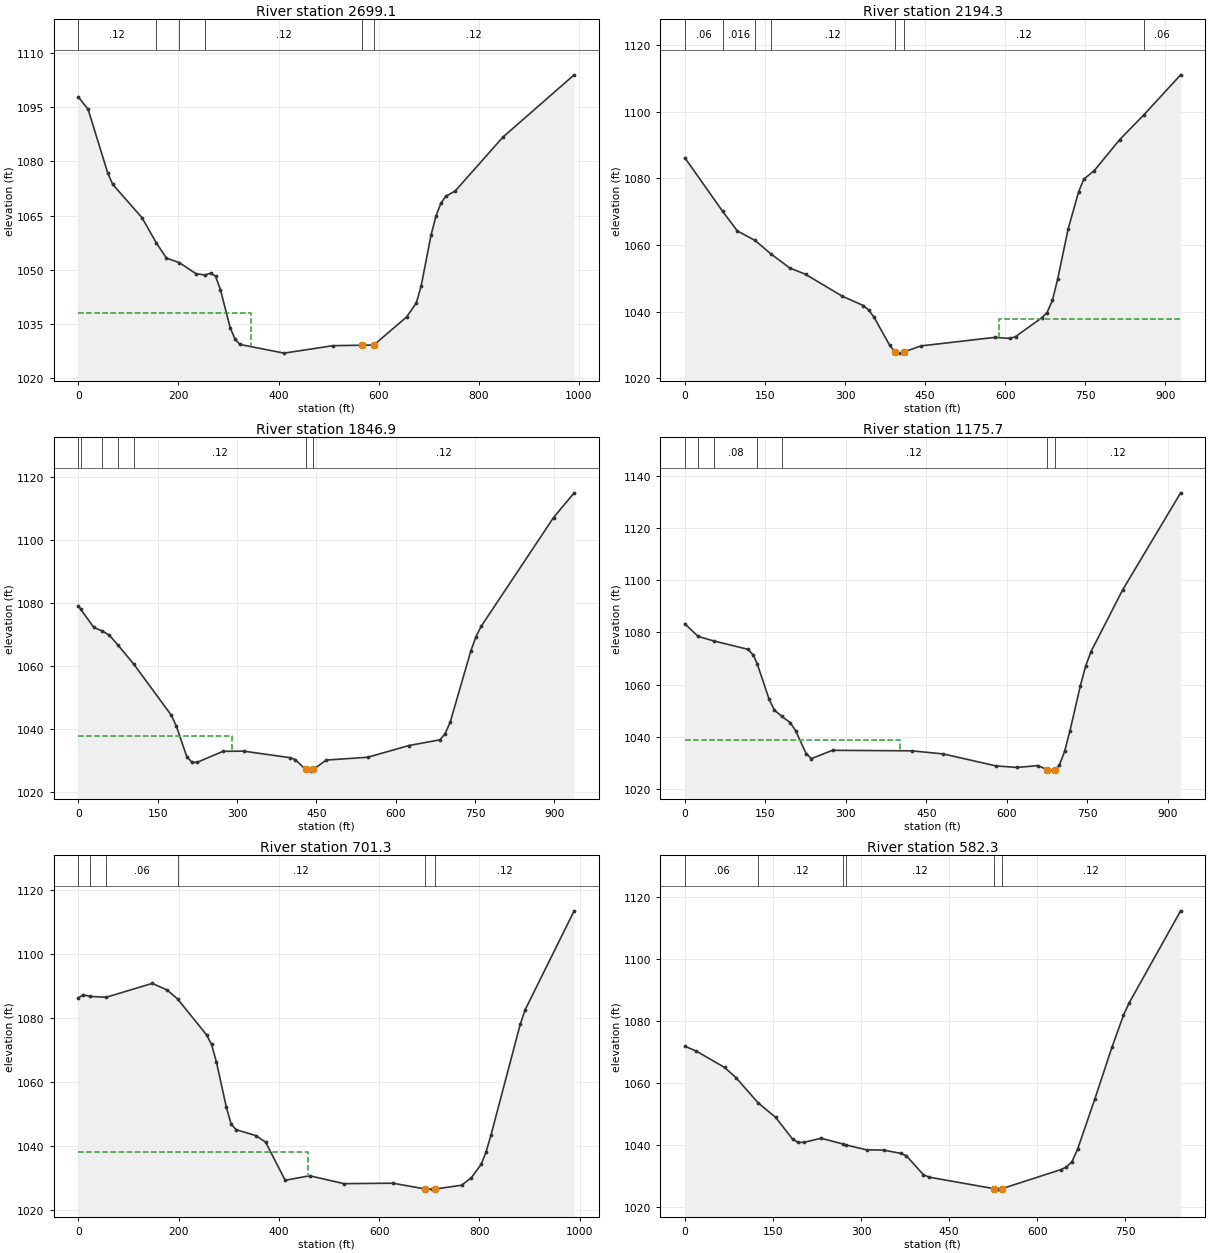
Type RM Length L Ch R = 1 ,2699.1  ,506.9,504.8,502.5
XS GIS Cut Line= 3
       1786642.4      267483.304     1787361.478       267672.76
     1787494.808      267880.431
#Sta/Elev= 30
       0 1097.89    19.6  1094.4    58.7 1076.81    68.5 1073.68   127.2 1064.41
  155.92 1057.41   176.1 1053.22  202.061051.956   234.8 1048.93  252.931048.548
   264.2 1049.07     274 1048.25   283.8 1044.52   303.3 1033.96   313.1 1030.78
   322.9 1029.32     411 1026.92   508.8 1028.99   567.5 1029.11  590.311029.164
   655.6 1036.93   675.1 1040.81   684.9 1045.58   704.5 1059.58   714.3 1064.81
     724 1068.39   733.8 1070.33   753.1 1071.87     848 1086.72   990.4 1103.98
#Mann= 6 ,-1 , 0
       0     .12       0  155.92    .016       0  202.06     .08       0
  252.93     .12       0   567.5    .045       0  590.31     .12       0
#XS Ineff= 2 , 0
          345.72 1037.91
Permanent Ineff=
       F       F
Bank Sta=567.5,590.31
XS Rating Curve= 0 ,0
Exp/Cntr=0.3,0.1

Type RM Length L Ch R = 1 ,2194.3  ,349.3,347.4,345.6
XS GIS Cut Line= 3
     1786581.614      267915.587     1787338.558      268038.851
     1787493.072      267991.976
#Sta/Elev= 30
       0 1086.22   70.611070.188    98.3 1064.26  131.531061.396     1611057.383
   196.6 1053.12   226.1 1051.23     295 1044.65   334.3 1041.86   344.1 1040.53
     354 1038.45   383.5 1029.97   393.3 1027.97   403.1 1027.58  410.691027.956
   442.4 1029.75   580.1  1032.3   609.6 1031.98   619.4 1032.56   668.6 1038.21
   678.4 1039.77   688.3 1043.39   698.1 1049.76   717.8 1064.82   737.4 1075.99
   747.2 1079.79   766.9 1082.38   814.4 1091.67  859.31 1099.04   928.4 1111.09
#Mann= 7 ,-1 , 0
       0     .06       0   70.61    .016       0  131.53     .08       0
     161     .12       0   393.3    .045       0  410.69     .12       0
  859.31     .06       0
#XS Ineff= 2 , 0
                          588.24         1037.74
Permanent Ineff=
       F       F
Bank Sta=393.3,410.69
XS Rating Curve= 0 ,0
Exp/Cntr=0.3,0.1

Type RM Length L Ch R = 1 ,1846.9  ,672.7,671.2,669.5
XS GIS Cut Line= 2
     1786553.836      268285.379     1787487.864       268365.24
#Sta/Elev= 30
       0 1079.07    4.651077.898    29.3 1072.18   45.461071.027    58.6 1069.71
   75.151066.543  104.841060.537   175.8 1044.34   185.5 1040.83   205.1 1031.15
   214.8 1029.42   224.6  1029.4   273.4 1032.88   312.5 1032.95   400.4 1030.87
   410.1 1030.28   429.5 1027.14   439.4 1026.61   444.5 1027.17   468.7 1030.12
   546.8    1031     625 1034.72   683.6 1036.54   693.3 1038.43   703.1 1042.17
   742.1 1064.75   751.9 1069.28   761.7 1072.55   898.4    1107   937.4 1114.85
#Mann= 7 ,-1 , 0
       0     .06       0    4.65    .016       0   45.46     .12       0
   75.15     .06       0  104.84     .12       0   429.5    .045       0
   444.5     .12       0
#XS Ineff= 2 , 0
          291.02 1037.74
Permanent Ineff=
       F       F
Bank Sta=429.5,444.5
XS Rating Curve= 0 ,0
Exp/Cntr=0.3,0.1

Type RM Length L Ch R = 1 ,1175.7  ,476,474.4,472.2
XS GIS Cut Line= 2
     1786522.586      268736.768     1787446.197      268750.657
#Sta/Elev= 30
       0 1083.31   24.911078.462   54.461076.711   117.9 1073.51   127.8 1071.27
  135.051067.882   157.2 1054.28     167 1050.18   180.61047.833   196.5 1045.38
   206.4 1042.32     226 1033.53   235.8 1031.59   275.2 1034.77   422.6 1034.57
   481.5 1033.38   579.8 1028.78   619.1  1028.2   658.4 1028.91  673.97 1027.38
   687.9 1026.78  690.541027.383   697.7 1029.02   707.5 1034.32   717.4 1042.15
     737 1059.62   746.8 1067.12   756.7 1072.64   815.6  1096.3   923.7 1133.57
#Mann= 7 ,-1 , 0
       0     .06       0   24.91    .016       0   54.46     .08       0
  135.05    .016       0   180.6     .12       0  673.97    .045       0
  690.54     .12       0
#XS Ineff= 2 , 0
          401.44 1038.85
Permanent Ineff=
       F       F
Bank Sta=673.97,690.54
XS Rating Curve= 0 ,0
Exp/Cntr=0.3,0.1

Type RM Length L Ch R = 1 ,701.3   ,129,119,109.3
XS GIS Cut Line= 3
     1786473.975      269104.823     1786769.114       269240.24
     1787432.308      269198.573
#Sta/Elev= 30
       0 1086.14     9.8 1087.18   22.78 1086.64   55.531086.369   147.6  1090.7
   177.1 1088.63  197.991085.844   255.8 1074.63   265.7 1071.64   275.5 1066.14
   295.2 1052.08     305 1046.65   314.9 1044.98     354 1043.14   373.6  1041.1
   412.7 1029.16   461.5 1030.58   529.9 1028.11   627.7 1028.25  691.941026.457
   705.8  1026.4  710.871026.405   764.5 1027.62     784 1029.96   803.6 1034.14
   813.3 1037.94   823.1 1043.21   881.7 1077.96   891.5 1082.48   989.2 1113.38
#Mann= 6 ,-1 , 0
       0     .06       0   22.78    .016       0   55.53     .06       0
  197.99     .12       0  691.94    .045       0  710.87     .12       0
#XS Ineff= 2 , 0
           458.2 1037.91
Permanent Ineff=
       F       F
Bank Sta=691.94,710.87
XS Rating Curve= 0 ,0
Exp/Cntr=0.3,0.1

Type RM Length L Ch R = 1 ,582.3   ,455.9,462.3,468.6
XS GIS Cut Line= 4
     1786710.086      269629.129     1787005.225      269410.379
     1787296.892      269254.129     1787442.725      269247.185
#Sta/Elev= 30
       0 1071.98    19.3 1070.43    67.7 1065.13      87 1061.87  125.011053.667
   154.7 1049.03   183.7 1041.95   193.4 1040.95     203 1040.97     232  1042.3
  268.881040.461  274.99 1040.09   309.4 1038.56   338.4 1038.47   367.4 1037.43
   377.1 1036.67   406.3 1030.52     416 1029.74  525.911026.042   532.8 1025.88
  539.951026.027   639.9 1032.15   649.6 1032.98   659.3 1034.76     669 1038.88
   698.2    1055   727.4 1071.73   746.9 1081.96   756.6 1085.96   844.2 1115.64
#Mann= 6 ,-1 , 0
       0     .06       0  125.01     .12       0  268.88     .06       0
  274.99     .12       0  525.91    .045       0  539.95     .12       0
Bank Sta=525.91,539.95
XS Rating Curve= 0 ,0
Exp/Cntr=0.3,0.1

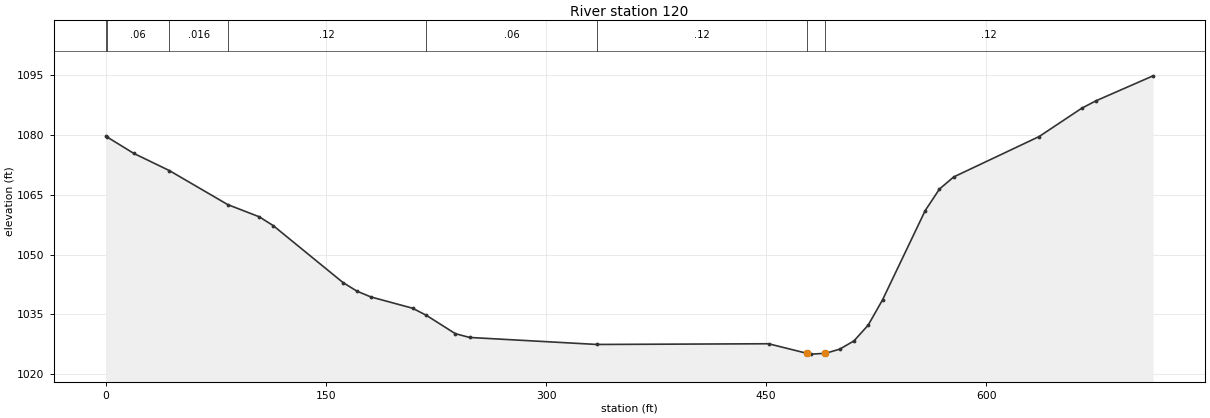
Type RM Length L Ch R = 1 ,120     ,111.3,120,128.7
XS GIS Cut Line= 3
     1786911.475      269913.851     1787081.614      269792.323
      1787574.67      269684.685
#Sta/Elev= 30
       0 1079.66     .541079.529      19 1075.36   43.331071.035   83.061062.517
   104.5 1059.47     114 1057.27   161.6 1042.99   171.1 1040.83   180.6 1039.38
   209.1 1036.54  218.491034.759   238.2 1030.17   247.9 1029.22  334.711027.463
   451.7 1027.64  477.711025.257   480.8 1025.04   490.5 1025.24   500.2 1026.29
   509.9 1028.35   519.6  1032.3   529.4 1038.65   558.5 1061.03   568.2 1066.42
   577.9 1069.45   636.1 1079.57   665.2 1086.68   674.9 1088.54   713.8  1094.8
#Mann= 8 ,-1 , 0
       0     .12       0     .54     .06       0   43.33    .016       0
   83.06     .12       0  218.49     .06       0  334.71     .12       0
  477.71    .045       0   490.5     .12       0
Bank Sta=477.71,490.5
XS Rating Curve= 0 ,0
Exp/Cntr=0.3,0.1

Chan Stop Cuts=-1
Use User Specified Reach Order=0
Composite Channel Slope=5